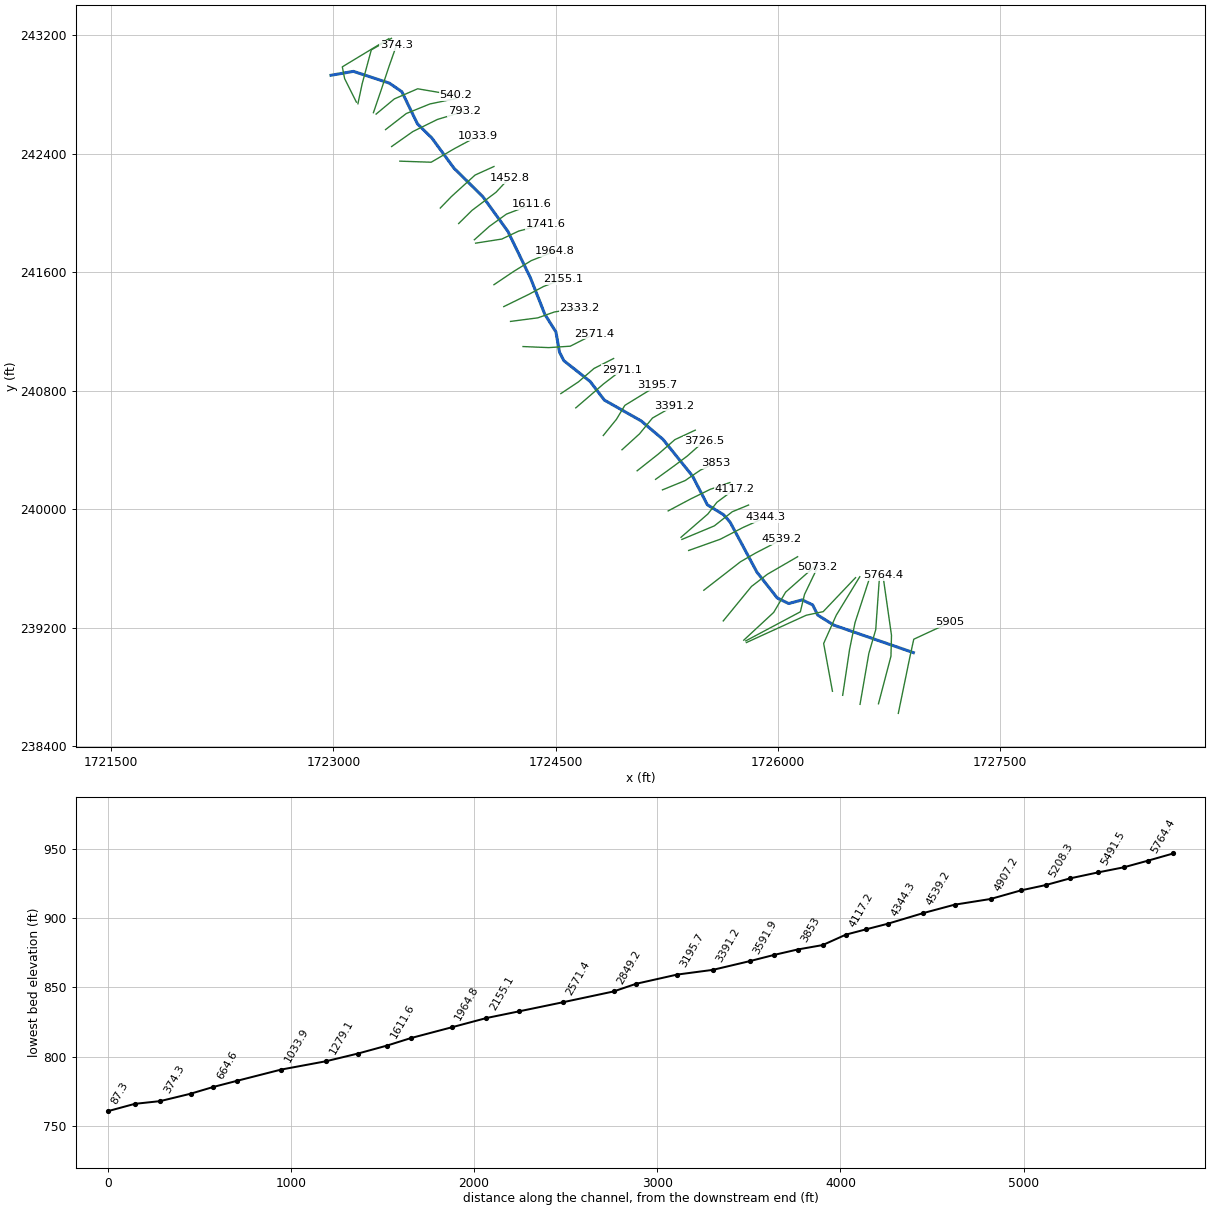
--- spccrk.prj (project) ---

Proj Title=spccrk
Current Plan=p01
Default Exp/Contr=0,0
English Units
Geom File=g01
Flow File=f01
Plan File=p01
BEGIN DESCRIPTION:
END DESCRIPTION:
DSS Export Rating Curves= 0
DSS Export Rating Curve Sorted= 0
DSS Export Volume Flow Curves= 0
DXF OffsetX= 0
DXF OffsetY= 0
DXF ScaleX= 0
DXF ScaleY= 0

--- spccrk.p01 (plan) ---

Plan Title=Floodplain
Program Version=4.00
Geom File=g01
Flow File=f01
K Sum by GR=0
Std Step Tol=0.01
Critical Tol=0.01
Num of Std Step Trials=20
Max Error Tol=0.3
Flow Tol Ratio=0.001
Split Flow NTrial=30
Split Flow Tol=0.02
Split Flow Ratio=0.02
Log Output Level=0
Friction Slope Method=1
Unsteady Friction Slope Method=2
Unsteady Bridges Friction Slope Method=1
Global Log Level=0
CheckData=False
Run HTab=0
Run UNet=0
Run PostProcess=0
UNET Theta=0
UNET Theta Warmup=0
UNET ZTol=0
UNET ZSATol=0
UNET MxIter=0
UNET MaxInSteps=0
UNET DtIC=0
UNET DtMin=0
UNET MaxCRTS=0
UNET WFStab=0
UNET SFStab=0
UNET WFX=0
UNET SFX=0
UNET DSS MLevel=0
UNET DZMax Abort=0
UNET Convert EG Bridges=0
UNET Use Existing IB Tables=0
UNET Froude Limit=0
UNET Froude Power=0
Write IC File=0
Echo Input=False
Echo Output=False
Write Detailed=0

--- spccrk.f01 (steady flow) ---

Flow Title=NFF Regression Equation
Program Version=4.00
Number of Profiles= 1
Profile Names=P100yr
River Rch & RM=spccrk,Main            ,5905
     317
River Rch & RM=spccrk,Main            ,5634.3
     442
River Rch & RM=spccrk,Main            ,4710
     467
River Rch & RM=spccrk,Main            ,2971.1
     517
River Rch & RM=spccrk,Main            ,540.2
     566
River Rch & RM=spccrk,Main            ,235.3
     659
Boundary for River Rch & Prof#=spccrk,Main            , 1
Up Type= 0
Dn Type= 3
Dn Slope=0.016
DSS Import GetInterval= 0
DSS Import GetPeak= 0
DSS Import FillOption= 0

--- spccrk.g01 (geometry) ---

Geom Title=USGS 10m DEM
Program Version=4.00

River Reach=spccrk          ,Main
Reach XY= 30
     1726916.102      239030.325     1726378.614      239216.166
     1726269.735      239283.992     1726236.136      239352.421
     1726165.586      239386.632     1726073.926      239361.944
     1725996.709      239399.451     1725858.904      239574.612
     1725678.736      239910.947     1725635.316      239961.092
     1725524.792      240028.936     1725424.249      240223.601
     1725224.843      240471.111     1725077.516      240595.818
     1724829.098      240736.216     1724733.034      240862.107
     1724555.763      241002.228     1724526.393      241059.937
     1724502.202      241196.225      1724427.72       241314.84
     1724329.045      241563.944     1724177.849      241875.547
     1724007.335      242111.694     1723813.987      242302.144
     1723664.393      242506.237     1723566.855      242602.296
     1723461.832      242819.107     1723377.052      242877.202
     1723134.898      242956.454     1722982.961      242930.069

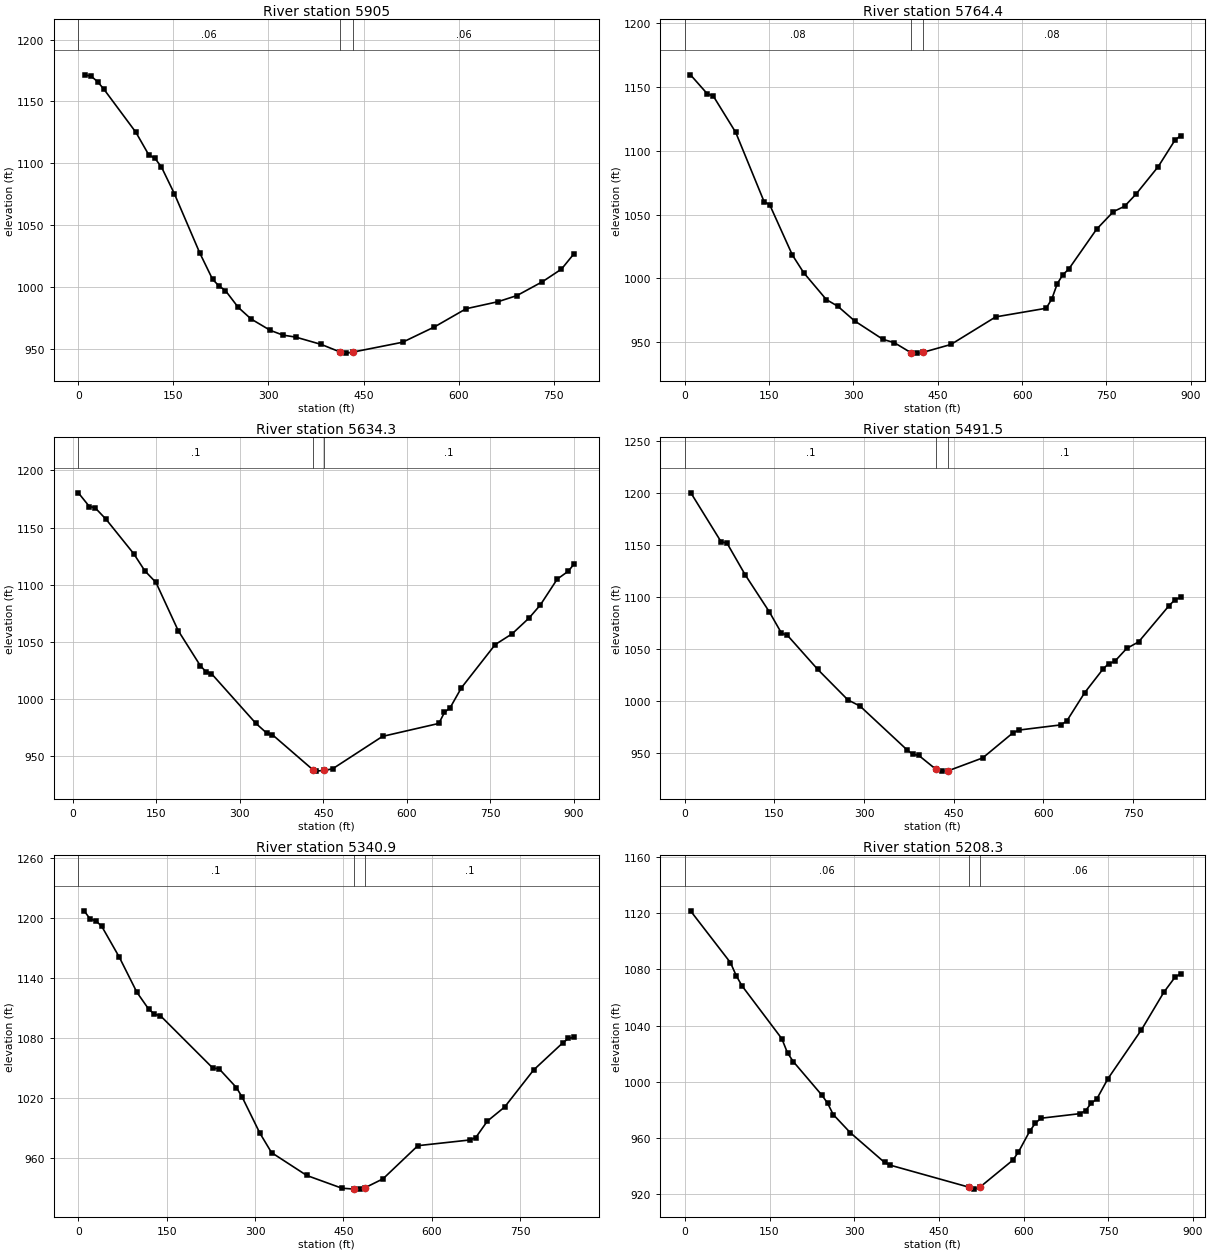
Type RM Length L Ch R = 1 ,5905    ,135.7,140.6,145.5
XS GIS Cut Line= 4
     1726814.127      238620.074     1726891.186      238995.736
     1726918.478      239120.957     1727164.103       239234.94
#Sta/Elev= 30
    10.1 1171.51    20.2 1170.38    30.3 1166.03    40.4 1159.84    90.8 1125.08
     111 1106.97   121.1 1103.91   131.2 1096.98   151.4 1075.62   191.7 1027.49
   211.9 1006.22     222 1000.94   232.1   997.2   252.3  983.63   272.5  974.27
   302.8  965.07   322.9  961.21   343.1  959.59   383.5  953.65   412.9   947.6
   422.9  946.65   432.9  947.45   511.6  955.44   561.8  967.79   611.9  982.52
   662.1  988.18   692.2  993.17   732.3 1004.34   762.4 1014.54   782.4 1027.12
#Mann= 3 , 0 , 0
       0     .06       0   412.9    .045       0   432.9     .06       0
Bank Sta=412.9,432.9
XS Rating Curve= 0 ,0
Exp/Cntr=0.3,0.1

Type RM Length L Ch R = 1 ,5764.4  ,136.7,130.1,123.4
XS GIS Cut Line= 4
     1726680.211      238684.892     1726764.494      239006.372
     1726768.106      239147.245     1726710.312      239551.805
#Sta/Elev= 30
    10.1 1159.51    40.3 1144.48    50.4 1143.07    90.6 1114.36     141 1060.12
   151.1 1057.58   191.4  1018.2   211.5 1004.37   251.8   983.3   271.9  978.18
   302.1  966.59   352.5  952.12   372.6  949.56   402.9  941.52   412.9  941.35
   422.9  941.87   473.3  948.13     553  969.76   642.7  976.52   652.7  983.68
   662.6  995.88   672.6 1002.91   682.6 1007.03   732.4 1038.46   762.3 1052.26
   782.3  1056.5   802.2 1065.81   842.1 1087.57     872 1108.43   881.9 1111.74
#Mann= 3 , 0 , 0
       0     .08       0   402.9    .045       0   422.9     .08       0
Bank Sta=402.9,422.9
XS Rating Curve= 0 ,0
Exp/Cntr=0.3,0.1

Type RM Length L Ch R = 1 ,5634.3  ,140.8,142.9,145
XS GIS Cut Line= 4
     1726555.659      238681.079     1726615.058      239024.634
     1726661.615      239185.173     1726688.906      239568.862
#Sta/Elev= 30
      10 1180.39    29.9 1168.35    39.8 1167.45    59.8 1157.21   109.6 1126.99
   129.5 1112.02   149.4 1101.91   189.3 1059.75   229.1 1028.97   239.1 1023.76
     249 1022.07   328.7  978.55   348.7  969.78   358.5  968.54  430.88     938
   437.1  936.63  451.21  937.24   466.6  938.62   556.3  967.06   657.5  978.41
   667.6  988.13   677.8  992.19     698 1009.64   758.7 1047.47   789.1 1056.91
   819.5 1070.73   839.7 1082.12   870.1 1104.81   890.3 1111.86   900.5 1118.27
#Mann= 3 , 0 , 0
      10      .1       0  430.88    .045       0  451.21      .1       0
Bank Sta=430.88,451.21
XS Rating Curve= 0 ,0
Exp/Cntr=0.3,0.1

Type RM Length L Ch R = 1 ,5491.5  ,156.1,150.6,145.1
XS GIS Cut Line= 4
     1726438.465      238742.084     1726485.022      239051.925
     1726521.946      239233.335     1726624.691      239547.992
#Sta/Elev= 30
    10.1 1200.58    60.6  1153.6    70.7  1152.1   101.1 1121.66   141.5 1086.02
   161.7 1065.64   171.8 1063.43   222.4 1030.74   272.9 1001.37   293.1  995.47
   371.8  953.32   381.5  949.04   391.3  948.04   420.2  934.62   430.2  932.88
   440.2  933.11   498.4   945.6   548.6  969.52   558.6  972.34   628.8  977.33
   638.9  980.98     669 1008.33   699.1 1030.64   709.1 1036.38   719.1 1038.34
   739.2 1050.87   759.2 1057.18   809.4 1091.53   819.4 1097.43   829.5  1100.1
#Mann= 3 , 0 , 0
       0      .1       0   420.2    .045       0   440.2      .1       0
Bank Sta=420.2,440.2
XS Rating Curve= 0 ,0
Exp/Cntr=0.3,0.1

Type RM Length L Ch R = 1 ,5340.9  ,156.5,132.6,108.8
XS GIS Cut Line= 4
     1726369.433      238769.376     1726310.034       239092.06
      1726395.12      239283.102     1726554.053      239543.176
#Sta/Elev= 30
     9.9 1207.01    19.9 1198.91    29.8 1197.02    39.8 1191.46    69.6 1160.62
    99.4 1125.57   119.3  1108.8   129.3 1103.46   139.2 1102.19   228.7 1049.53
   238.6 1049.28   268.4 1030.25   278.4 1020.47   308.2  984.72   328.1  965.16
   387.9   942.3   447.6  929.55   467.5  928.71   477.5  928.63   487.5  930.22
   517.3  938.89   576.6   972.1   665.1  977.82   674.9  980.19   694.6  996.66
     724 1010.79   773.2 1047.84   822.4 1074.81   832.2 1079.37     842 1080.56
#Mann= 3 , 0 , 0
       0      .1       0   467.5    .045       0   487.5      .1       0
Bank Sta=467.5,487.5
XS Rating Curve= 0 ,0
Exp/Cntr=0.3,0.1

Type RM Length L Ch R = 1 ,5208.3  ,106.5,135.1,163.6
XS GIS Cut Line= 4
     1725788.281      239098.482      1726192.84      239283.102
     1726306.823      239307.183     1726525.156      239536.754
#Sta/Elev= 30
    10.1 1121.54    80.9  1084.7      91 1075.54   101.1 1068.35   171.8 1030.71
   181.9 1020.56     192 1014.48   242.6  990.64   252.7  984.99   262.8  976.82
   293.1   963.9   353.7  942.78   363.8  940.83   502.7  925.25   512.7  923.81
   522.7  925.25     581  944.44   590.9  950.23   610.7  964.94   620.6  970.54
   630.5  974.17   699.8  977.44   709.7  979.58   719.6  984.82   729.5  987.82
   749.3 1002.29   808.7 1037.07   848.3 1063.71   868.1  1074.4     878 1076.81
#Mann= 3 , 0 , 0
       0     .06       0   502.7    .045       0   522.7     .06       0
Bank Sta=502.7,522.7
XS Rating Curve= 0 ,0
Exp/Cntr=0.3,0.1

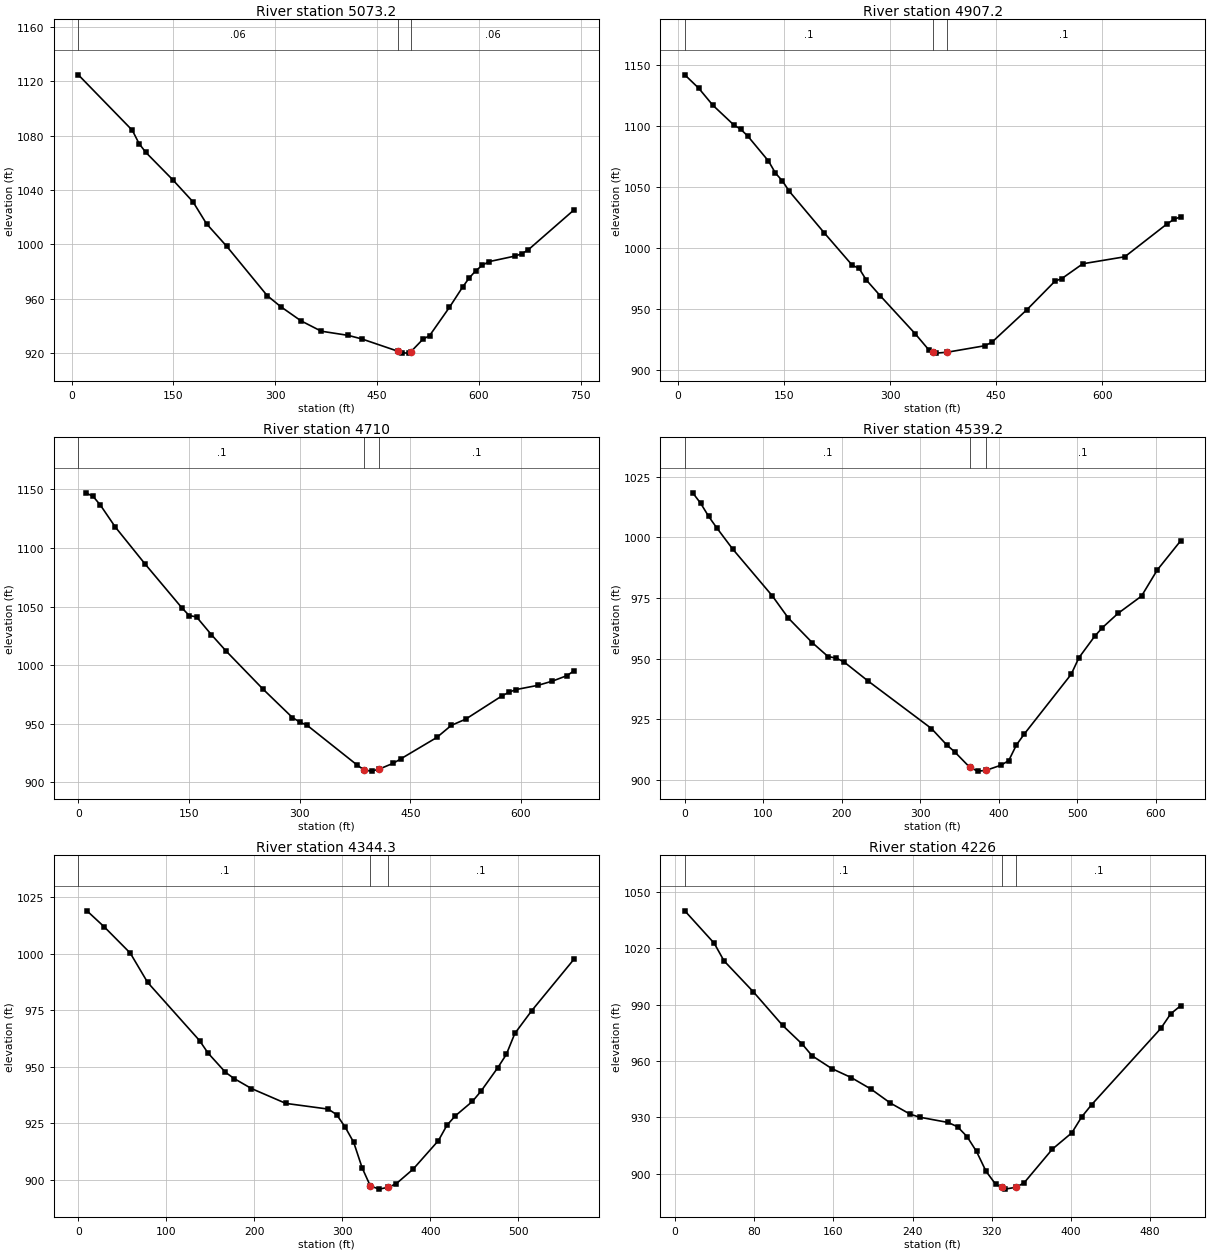
Type RM Length L Ch R = 1 ,5073.2  ,172.9,166,158.8
XS GIS Cut Line= 4
     1725784.401       239109.92     1726152.839      239306.179
     1726180.532      239422.972     1726268.427      239605.987
#Sta/Elev= 30
     9.9 1124.68    89.5 1083.84    99.4 1074.09   109.3 1067.66   149.1 1047.44
   178.9 1031.24   198.8 1015.11   228.6  998.52   288.2  962.26   308.1  954.17
   337.9  943.75   367.8  936.11   407.5  933.03   427.5  930.43  480.26  921.46
   487.5  920.15   497.5  919.97  500.08  921.09   517.5  930.11   527.5  932.86
   556.8  953.72   576.2   968.6   585.8  975.21   595.5  980.58   605.2   984.6
   614.8  987.24   653.5  991.39   663.2  993.04   672.8  995.93   740.5 1025.43
#Mann= 3 , 0 , 0
     9.9     .06       0  480.26    .045       0  500.08     .06       0
Bank Sta=480.26,500.08
XS Rating Curve= 0 ,0
Exp/Cntr=0.3,0.1

Type RM Length L Ch R = 1 ,4907.2  ,206.9,197.1,187.4
XS GIS Cut Line= 4
     1725770.621      239114.536     1725972.901      239302.367
     1726053.171      239438.825     1726260.266       239621.84
#Sta/Elev= 30
     9.9 1142.13    29.6 1131.13    49.3 1117.32    78.9 1101.14    88.7 1097.58
    98.6 1092.07   128.2 1071.37     138 1061.52   147.9 1055.02   157.7 1046.49
     207 1012.45   246.5  985.92   256.3  983.25   266.2  973.94   285.9  960.98
   335.4  929.75   355.1  916.22  360.41  914.93   365.1  913.76  380.34  914.46
   434.4  919.87   444.2  922.84   493.6  949.48   533.1  972.78   542.9  974.99
   572.5   987.1   631.8  992.83     691 1019.58   700.9 1023.43   710.7 1025.64
#Mann= 3 , 0 , 0
     9.9      .1       0  360.41    .045       0  380.34      .1       0
Bank Sta=360.41,380.34
XS Rating Curve= 0 ,0
Exp/Cntr=0.3,0.1

Type RM Length L Ch R = 1 ,4710    ,174.1,170.8,167.5
XS GIS Cut Line= 4
     1725632.156      239244.773     1725822.395      239477.154
     1725930.759      239560.233     1726134.243      239678.229
#Sta/Elev= 30
      10 1147.13      20 1144.12      30 1136.55    50.1 1117.94    90.1 1086.67
   140.1 1049.16   150.2 1042.43   160.2 1041.23   180.2 1026.19   200.2 1012.17
   250.3  979.63   290.3  955.29   300.3  951.46   310.1  948.75   378.3  914.63
   387.9  910.38   397.9  909.62   407.9  911.38   427.1   916.4   436.9  920.02
   485.9  938.35   505.5  948.64   525.1  953.99   574.1  973.78   583.9  977.04
   593.7  979.28   623.1  982.85   642.7  986.46   662.3   991.1   672.1  995.31
#Mann= 3 , 0 , 0
       0      .1       0   387.9    .045       0   407.9      .1       0
Bank Sta=387.9,407.9
XS Rating Curve= 0 ,0
Exp/Cntr=0.3,0.1

Type RM Length L Ch R = 1 ,4539.2  ,196.1,194.9,193.7
XS GIS Cut Line= 4
     1725500.915      239451.869     1725748.949      239644.516
     1725851.293      239703.514     1726028.287      239795.022
#Sta/Elev= 30
    10.1 1018.31    20.3 1013.95    30.4 1008.58    40.5 1003.95    60.8  995.21
   111.4  975.84   131.7  966.73   162.1   956.6   182.4  950.81   192.5  950.19
   202.6  948.63     233  940.82   314.1  921.13   333.7  914.33   343.6  911.54
   363.1  905.07   373.1  903.57   383.1  903.84   402.7  906.02   412.5  907.91
   422.3  914.36   432.2  918.83     492  943.48   501.9  950.33   521.9  959.14
   531.8  962.73   551.7  968.61   581.6  975.74   601.6  986.48   631.4  998.51
#Mann= 3 , 0 , 0
       0      .1       0   363.1    .045       0   383.1      .1       0
Bank Sta=363.1,383.1
XS Rating Curve= 0 ,0
Exp/Cntr=0.3,0.1

Type RM Length L Ch R = 1 ,4344.3  ,113.6,118.4,123.2
XS GIS Cut Line= 4
     1725398.571      239720.371     1725611.687      239796.226
     1725765.805      239875.693     1725915.107      239943.119
#Sta/Elev= 30
     9.8 1018.99    29.5 1011.87      59 1000.29    78.7  987.33   137.7  961.58
   147.5  955.98   167.2  947.52     177  944.77   196.7  940.34   235.8  933.76
     284  931.24   293.6  928.75   303.3  923.19   312.9  916.53   322.5  905.22
   331.8  897.22   341.8  895.82   351.8  896.61   361.1  898.18   380.3  904.61
   409.2  917.32   418.9  924.13   428.5   928.3   447.8  934.65   457.4  939.09
   476.7  949.61   486.3  955.42     496  964.73   515.3  974.85   563.4  997.67
#Mann= 3 , 0 , 0
       0      .1       0   331.8    .045       0   351.8      .1       0
Bank Sta=331.8,351.8
XS Rating Curve= 0 ,0
Exp/Cntr=0.3,0.1

Type RM Length L Ch R = 1 ,4226    ,102.6,108.7,114.8
XS GIS Cut Line= 4
     1725352.818      239795.022     1725571.954      239886.529
     1725692.359      239981.649     1725803.131      240027.402
#Sta/Elev= 30
     9.9 1039.93    39.6 1022.67    49.5 1013.32    79.2  996.79   108.8   978.9
   128.6  968.95   138.5  962.77   158.3  955.99   178.1  951.16   197.9  945.08
   217.7  937.57   237.5  931.71   247.1  930.09   275.8  927.29   285.4  925.01
     295  919.79   304.6  911.85   314.2  901.32   323.8  894.48  330.16  892.69
   333.4   891.8  344.42  892.79   352.6  895.11   381.3  913.13   400.9  921.77
   410.9  930.28   420.9  936.76   490.8  977.35   500.8  985.13   510.8   989.4
#Mann= 3 , 0 , 0
     9.9      .1       0  330.16    .045       0  344.42      .1       0
Bank Sta=330.16,344.42
XS Rating Curve= 0 ,0
Exp/Cntr=0.3,0.1

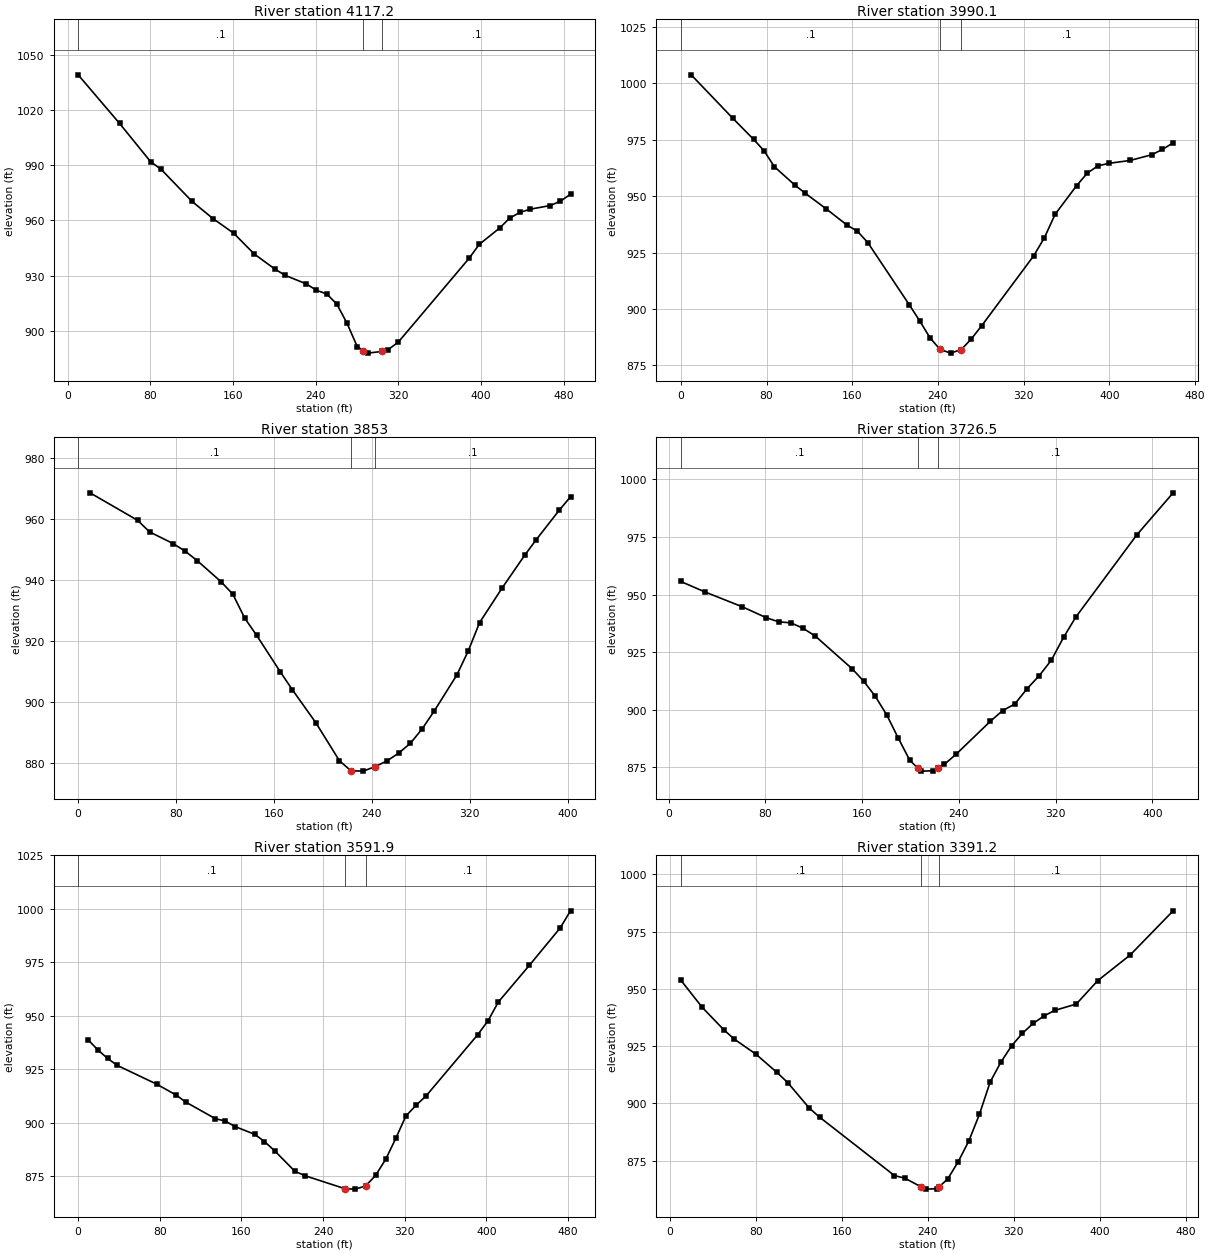
Type RM Length L Ch R = 1 ,4117.2  ,138.6,127.1,115.7
XS GIS Cut Line= 4
     1725346.798       239809.47     1725528.608        239967.2
     1725588.811      240045.463     1725706.807      240133.358
#Sta/Elev= 30
      10 1039.05    50.1 1012.66    80.2  991.86    90.3  987.76   120.3  970.33
   140.4  961.08   160.5  953.12   180.5  941.79   200.6  933.57   210.6  930.18
   230.7  925.62   240.7  922.12   250.6  920.15   260.4  914.62   270.3  904.19
   280.2  891.53  285.99   889.4   290.1  888.02  304.33  888.94   309.8  889.84
   319.7  893.85   388.5  939.52   398.3  947.05   417.9  955.85   427.7  961.26
   437.5  964.35   447.3   966.1     467  968.11   476.8  970.47   486.6  974.26
#Mann= 3 , 0 , 0
      10      .1       0  285.99    .045       0  304.33      .1       0
Bank Sta=285.99,304.33
XS Rating Curve= 0 ,0
Exp/Cntr=0.3,0.1

Type RM Length L Ch R = 1 ,3990.1  ,133.4,137.1,140.7
XS GIS Cut Line= 4
     1725260.106      239987.669     1725414.224      240069.544
     1725544.261      240133.358     1725676.706      240179.112
#Sta/Elev= 30
     9.7 1003.75    48.5  984.52    67.9  975.18    77.6  970.19    87.3  963.06
   106.6  954.85   116.3  951.24   135.7  944.39   155.1  937.19   164.8  934.49
   174.5  929.45   213.1     902   222.8  894.88   232.5  887.32   241.8  882.17
   251.8  880.47   261.8  882.06   271.1  886.73   280.7  892.53   329.4   923.6
   339.4  931.63   349.4     942   369.4  954.65   379.4  960.24   389.4  963.44
   399.4  964.53   419.5  965.83   439.5  968.35   449.5  970.71   459.5  973.62
#Mann= 3 , 0 , 0
       0      .1       0   241.8    .045       0   261.8      .1       0
Bank Sta=241.8,261.8
XS Rating Curve= 0 ,0
Exp/Cntr=0.3,0.1

Type RM Length L Ch R = 1 ,3853    ,125.5,126.6,127.6
XS GIS Cut Line= 4
     1725221.577      240129.746     1725374.491      240192.357
     1725478.038      240263.395     1725579.178      240310.353
#Sta/Elev= 30
     9.7   968.7    48.6  959.66    58.3  955.88    77.8  951.98    87.5  949.51
    97.2  946.45   116.6  939.55   126.4   935.4   136.1  927.53   145.8  921.91
   165.2  909.86   174.9  904.08   194.2  893.18   213.5  880.68   222.9  877.39
   232.9  877.27   242.9  878.79   252.2   880.6   261.8  883.14   271.5  886.43
   281.1  891.16   290.8  896.92   309.4  908.83   318.7  916.71     328  926.06
   346.6  937.54   365.1  948.32   374.4  953.36     393  962.94   402.3  967.39
#Mann= 3 , 0 , 0
       0      .1       0   222.9    .045       0   242.9      .1       0
Bank Sta=222.9,242.9
XS Rating Curve= 0 ,0
Exp/Cntr=0.3,0.1

Type RM Length L Ch R = 1 ,3726.5  ,132.7,134.5,136.4
XS GIS Cut Line= 4
     1725175.154      240200.785     1725297.967      240289.884
     1725389.474      240358.515     1725502.654       240458.45
#Sta/Elev= 30
    10.1  955.67    30.3  951.08    60.7  944.75    80.9  939.93      91  938.18
   101.2  937.72   111.3  935.35   121.4  931.94   151.7  917.83   161.3  912.42
   170.8  905.92   180.3  897.85   189.9   887.7   199.4  878.11  206.36   874.6
   208.9  873.41   218.5  873.54  222.43  874.57     228  876.38   237.5  880.64
   266.1  895.08   276.2  899.69   286.2   902.5   296.3  909.12   306.4  914.81
   316.4  921.53   326.5  931.41   336.6   940.2   386.9  975.78   417.1  994.13
#Mann= 3 , 0 , 0
    10.1      .1       0  206.36    .045       0  222.43      .1       0
Bank Sta=206.36,222.43
XS Rating Curve= 0 ,0
Exp/Cntr=0.3,0.1

Type RM Length L Ch R = 1 ,3591.9  ,196.5,200.7,204.9
XS GIS Cut Line= 4
     1725050.602      240258.579     1725193.884      240371.759
      1725305.86      240469.287     1725443.121      240533.101
#Sta/Elev= 30
     9.6  938.76    19.2  934.04    28.8  930.01    38.4  926.72    76.9  917.98
    96.1  912.84   105.7  909.52   134.5  901.81   144.2  900.71   153.8  898.11
     173  894.51   182.6  891.13   192.5  886.82   212.3  877.26   222.2  875.17
   261.7  869.02   271.7  868.87   281.7  870.35   291.5  875.29   301.4  882.83
   311.3  892.64   321.2  903.09   331.1  908.04   341.2  912.59   391.6  941.11
   401.7  947.64   411.8  956.39   442.1  973.49   472.4  991.03   482.5  999.03
#Mann= 3 , 0 , 0
       0      .1       0   261.7    .045       0   281.7      .1       0
Bank Sta=261.7,281.7
XS Rating Curve= 0 ,0
Exp/Cntr=0.3,0.1

Type RM Length L Ch R = 1 ,3391.2  ,191.9,195.5,199.1
XS GIS Cut Line= 4
     1724948.259      240400.656     1725066.255      240507.816
      1725154.15      240614.976     1725302.248       240699.26
#Sta/Elev= 30
      10  953.86    29.9  941.99    49.8  932.27    59.8  928.08    79.7  921.61
    99.6  913.52   109.6  909.08   129.5  898.04   139.5  893.91   208.9  868.52
   218.8  867.32  233.69   863.6   238.6  862.59   248.5  862.77  250.55  863.64
   258.4  866.95   268.3  874.56   278.2  883.65   288.1  895.32     298  909.31
     308  918.04     318  925.13   328.1  930.67   338.1  934.95   348.1  938.19
   358.1  940.62   378.2   943.4   398.2  953.62   428.3  964.78   468.4  984.11
#Mann= 3 , 0 , 0
      10      .1       0  233.69    .045       0  250.55      .1       0
Bank Sta=233.69,250.55
XS Rating Curve= 0 ,0
Exp/Cntr=0.3,0.1

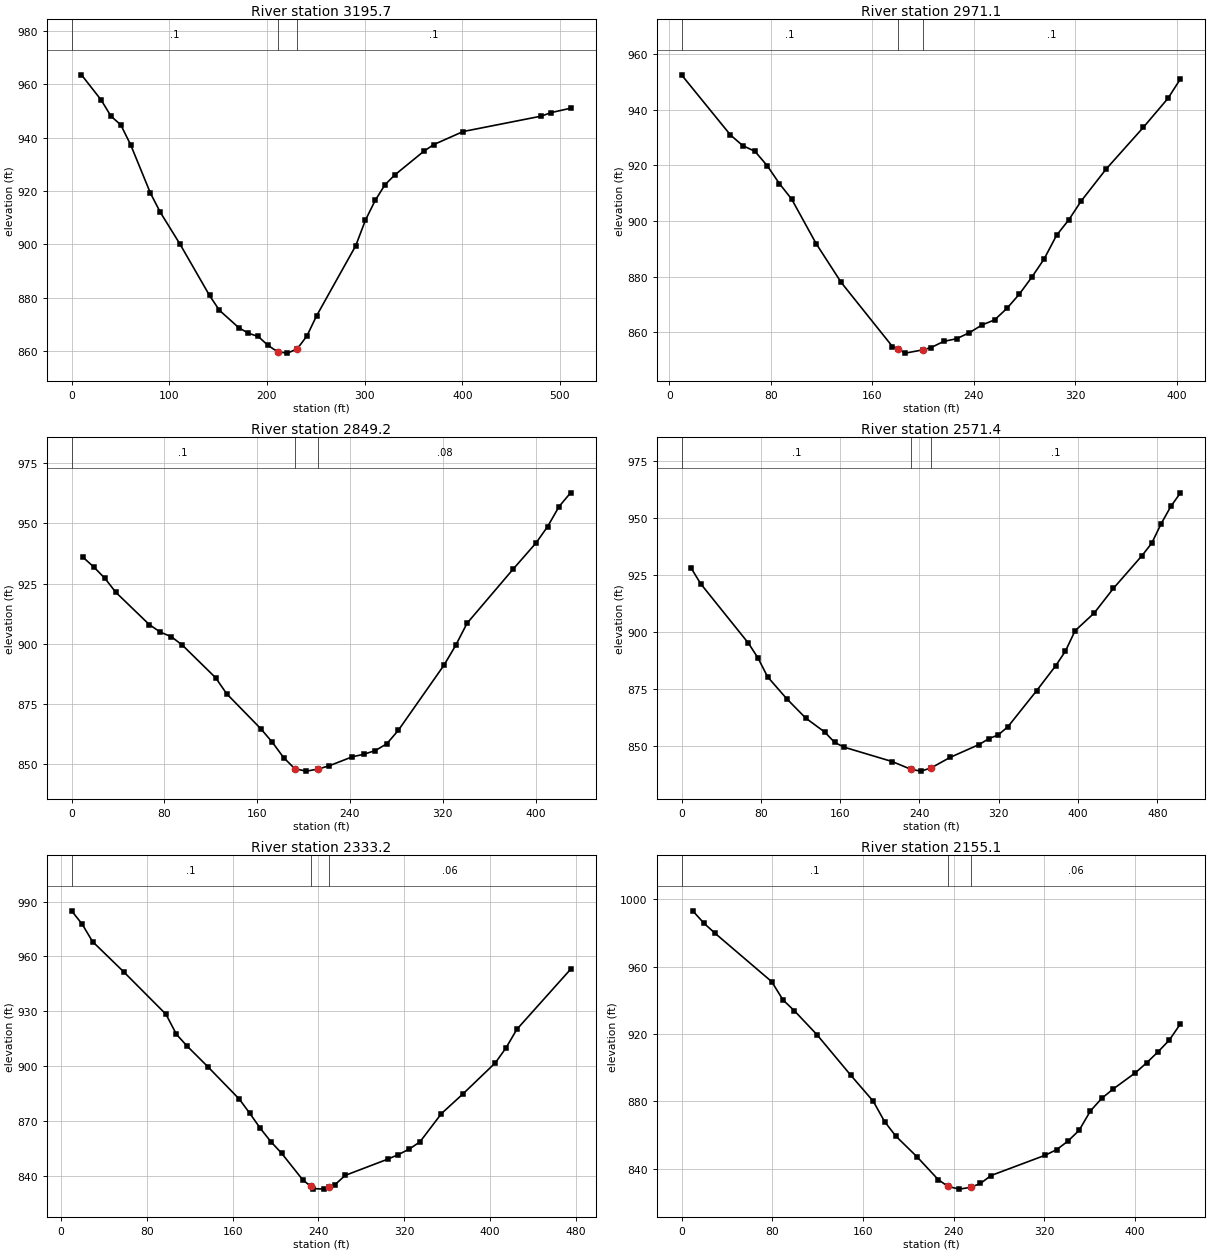
Type RM Length L Ch R = 1 ,3195.7  ,232.5,224.6,216.7
XS GIS Cut Line= 4
     1724821.834       240496.98     1724910.933      240606.548
     1724967.523      240700.464     1725189.068      240836.521
#Sta/Elev= 30
    10.1  963.55    30.3  954.09    40.3  948.04    50.4  944.76    60.5  937.27
    80.7  919.18    90.8     912     111  900.04   141.2  880.81   151.2  875.29
   171.1  868.72   181.1  866.62   191.1  865.42     201   862.1     211  859.67
     221  859.17     231  860.76   240.9  865.59   250.9  873.21   290.9  899.44
   300.9  909.07   310.9  916.48   320.9  922.33   330.9  925.99   360.9  934.96
   370.9   937.4   400.9  942.28   480.9  948.06   490.9  949.37   510.9  951.02
#Mann= 3 , 0 , 0
       0      .1       0     211    .045       0     231      .1       0
Bank Sta=211,231
XS Rating Curve= 0 ,0
Exp/Cntr=0.3,0.1

Type RM Length L Ch R = 1 ,2971.1  ,122,121.9,121.8
XS GIS Cut Line= 4
     1724636.411      240683.607      1724731.53      240765.482
     1724823.038      240844.949     1724947.055      240940.069
#Sta/Elev= 30
     9.7  952.61    48.3  930.96    57.9  927.16    67.6  925.08    77.2  919.95
    86.9  913.46    96.5  907.91   115.8  891.91   135.6  877.91     176  854.85
  180.27  853.89   186.1   852.5  199.99  853.68   206.3  854.48   216.4  856.72
   226.5  857.68   236.6  859.85   246.7  862.66   256.5  864.46   266.2   868.6
     276  873.73   285.8  879.81   295.5  886.34   305.3  894.86   315.1  900.53
   324.8  907.25   344.4  918.71   373.7  933.69   393.2  944.18     403  951.16
#Mann= 3 , 0 , 0
     9.7      .1       0  180.27    .045       0  199.99      .1       0
Bank Sta=180.27,199.99
XS Rating Curve= 0 ,0
Exp/Cntr=0.3,0.1

Type RM Length L Ch R = 1 ,2849.2  ,293.9,277.8,261.6
XS GIS Cut Line= 4
     1724535.271       240779.93     1724654.472      240859.397
     1724759.223      240949.701     1724891.668      241017.127
#Sta/Elev= 30
     9.6  936.02    19.1  931.91    28.7  927.17    38.2  921.32    66.9  907.97
    76.4  904.82      86  902.89    95.5  899.39   124.2  885.82   133.7  879.17
     163  864.68   172.9  859.11   182.8  852.62   192.5  847.97   202.5     847
   212.5  847.86   222.3  849.26     242  852.95   251.9  854.01   261.8  855.54
   271.7  858.35   281.6  863.91   321.2  891.16   331.1  899.25     341  908.52
   380.6  930.95   400.5  941.92   410.4  948.69   420.3  957.04   430.2  962.73
#Mann= 3 , 0 , 0
       0      .1       0   192.5    .045       0   212.5     .08       0
Bank Sta=192.5,212.5
XS Rating Curve= 0 ,0
Exp/Cntr=0.3,0.1

Type RM Length L Ch R = 1 ,2571.4  ,231.4,238.2,245
XS GIS Cut Line= 4
     1724280.014      241097.798     1724453.396      241090.574
     1724599.086      241100.207     1724762.836      241183.286
#Sta/Elev= 30
     9.6  928.25    19.3  921.32    67.5  895.24    77.1  888.78    86.8  880.52
     106  870.94   125.3  862.41   144.6  856.24   154.3  851.79   163.9  849.68
   212.5  843.36   231.7  839.91   241.7  839.17   251.7  840.58   270.9  845.19
   300.1  850.83   309.8  853.34   319.5  855.08   329.2  858.64   358.2  874.46
   377.5  885.44   387.2  891.78   396.9   900.7   416.2  908.46   435.5  919.24
   464.5  933.67   474.2  939.08   483.8  947.69   493.5  955.21   503.2  961.16
#Mann= 3 , 0 , 0
       0      .1       0   231.7    .045       0   251.7      .1       0
Bank Sta=231.7,251.7
XS Rating Curve= 0 ,0
Exp/Cntr=0.3,0.1

Type RM Length L Ch R = 1 ,2333.2  ,174.2,178.1,182
XS GIS Cut Line= 4
     1724195.731      241267.569     1724379.949       241291.65
     1724491.926      241331.383     1724660.492      241357.872
#Sta/Elev= 30
     9.8  984.99    19.6  977.73    29.3  968.18    58.7  951.41    97.8  928.37
   107.6  917.37   117.3  911.09   136.9  899.62   166.2  881.93     176  874.14
   185.8  865.92   195.7  858.59   205.6  852.33   225.4  837.72  232.72  834.24
   235.3  832.95   245.2  832.64  249.96  833.68   255.1  834.88     265  840.16
   304.6  849.03   314.6  851.54   324.7  854.56   334.7   858.5   354.8  874.02
   374.9   884.8     405  901.76     415  909.97   425.1  920.12   475.2  952.98
#Mann= 3 , 0 , 0
     9.8      .1       0  232.72    .045       0  249.96     .06       0
Bank Sta=232.72,249.96
XS Rating Curve= 0 ,0
Exp/Cntr=0.3,0.1

Type RM Length L Ch R = 1 ,2155.1  ,188.9,190.4,191.8
XS GIS Cut Line= 4
     1724149.977      241367.505     1724319.747      241450.584
     1724418.479      241503.562     1724548.516      241552.927
#Sta/Elev= 30
     9.9  993.09    19.9  985.63    29.8  979.63    79.6  950.99    89.5  940.17
    99.5  933.76   119.4  919.58   149.2  895.53   169.1  880.02   179.1  867.94
     189  859.32   207.7  847.02   226.4  833.48     235  829.43     245  827.81
     255  828.88   263.7   831.2     273  835.88   320.9  847.97   330.9  851.27
   340.8   856.3   350.7  862.72   360.7  874.27   370.6  881.68   380.5  887.15
   400.4  896.94   410.3  902.85   420.3  909.33   430.2  916.27   440.1  925.97
#Mann= 3 , 0 , 0
       0      .1       0     235    .045       0     255     .06       0
Bank Sta=235,255
XS Rating Curve= 0 ,0
Exp/Cntr=0.3,0.1

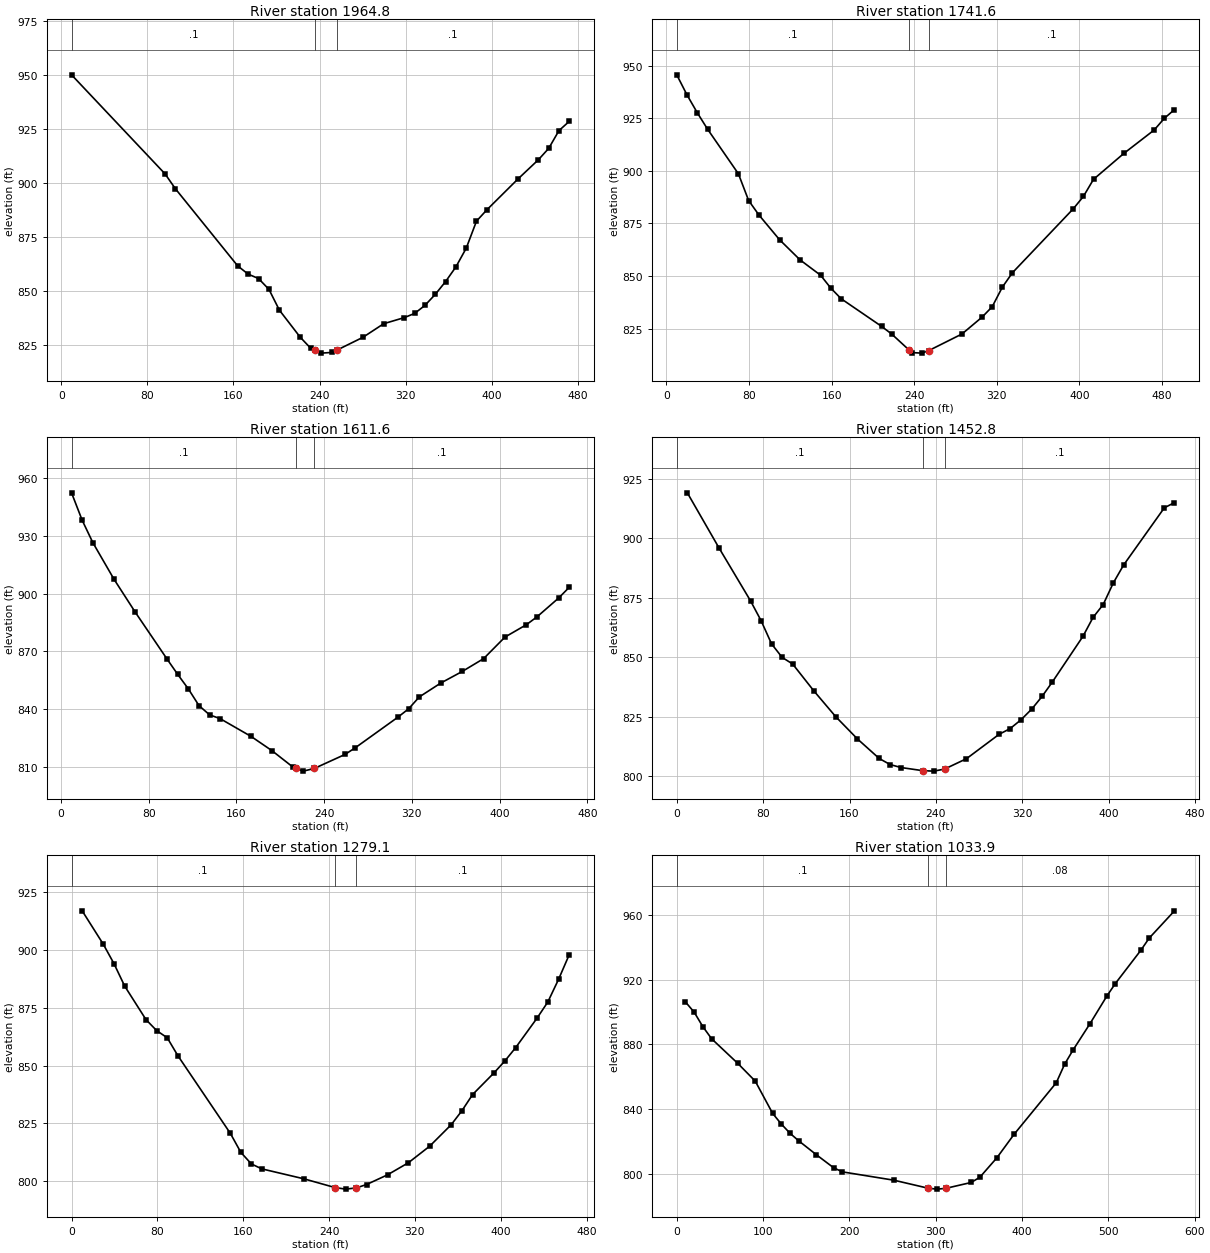
Type RM Length L Ch R = 1 ,1964.8  ,225.9,223.2,220.4
XS GIS Cut Line= 4
     1724083.754      241515.602     1724219.811       241607.11
       1724335.4      241678.148     1724495.538      241741.962
#Sta/Elev= 30
     9.6  950.13    96.5  904.18   106.1  897.29     164  861.51   173.7  857.71
   183.3  855.68     193  850.65   202.7  841.01   222.1  828.44   231.8  823.34
  235.92  822.37   241.5  821.09   251.2   821.4  256.08  822.47   280.3  828.42
   299.6  834.73   318.8  837.57   328.4  839.52   337.9  843.22   347.5  848.32
   357.1  854.27   366.7  861.09   376.3  869.77   385.8  882.29   395.4  887.51
   424.1  901.72   443.3  910.75   452.9  916.02   462.4  924.25     472  928.56
#Mann= 3 , 0 , 0
     9.6      .1       0  235.92    .045       0  256.08      .1       0
Bank Sta=235.92,256.08
XS Rating Curve= 0 ,0
Exp/Cntr=0.3,0.1

Type RM Length L Ch R = 1 ,1741.6  ,125.5,130,134.5
XS GIS Cut Line= 4
     1723959.738      241796.145     1724136.732      241823.838
     1724251.116       241878.02     1724431.723      241923.773
#Sta/Elev= 30
      10  945.65    19.9  936.12    29.9   927.6    39.8  919.83    69.7  898.58
    79.6  885.88    89.6  878.98   109.5  867.26   129.4  857.65   149.3  850.34
   159.2  844.21   169.2  839.17   208.4  826.01   218.1   822.4  235.01  814.77
   237.6  813.56   247.3   813.3  253.98  814.49   286.2   822.4   305.7  830.43
   315.5  835.37   325.3  844.67   335.1  851.54     394  881.94   403.8  887.81
   413.6  895.95     443  908.28   472.4  919.43   482.2  924.97     492  929.13
#Mann= 3 , 0 , 0
      10      .1       0  235.01    .045       0  253.98      .1       0
Bank Sta=235.01,253.98
XS Rating Curve= 0 ,0
Exp/Cntr=0.3,0.1

Type RM Length L Ch R = 1 ,1611.6  ,158.2,158.8,159.3
XS GIS Cut Line= 4
     1723951.309      241819.022     1724052.449      241909.325
     1724168.037      241992.404      1724341.42      242058.626
#Sta/Elev= 30
     9.7  952.21    19.4  937.97    29.1   926.4    48.4  907.41    67.8   890.3
    96.8  865.98   106.5  858.05   116.2  850.52   125.9  841.86   135.6  837.05
   145.1  835.13   173.5  825.85   192.5  818.47   211.5  810.01  214.71  809.26
     221  807.89     231  809.27     259  816.53   268.4     820   307.2  835.84
     317  840.19   326.8  846.38   346.3  853.55   365.9  859.57   385.4  866.22
   404.9  877.41   424.5  883.86   434.2  887.95   453.8  897.65   463.5  903.23
#Mann= 3 , 0 , 0
     9.7      .1       0  214.71    .045       0     231      .1       0
Bank Sta=214.71,231
XS Rating Curve= 0 ,0
Exp/Cntr=0.3,0.1

Type RM Length L Ch R = 1 ,1452.8  ,171.4,173.7,176
XS GIS Cut Line= 4
     1723845.353       241928.59     1723935.657      242017.689
     1724096.999      242139.297     1724187.302      242235.621
#Sta/Elev= 30
     9.8  919.15      39  896.08    68.3  873.75    78.1  865.39    87.8  855.64
    97.6  849.95   107.3  847.19   126.9  835.91   147.1  825.09   167.3  815.68
   187.5  807.45   197.6   804.9   207.7  803.65     228  802.32     238  802.14
     248     803   268.3  807.37   298.6  817.65   308.7  820.01   318.8  823.73
   328.9  828.31   338.3  833.55   347.8  839.61   376.1  858.77   385.5  866.76
   394.9  872.18   404.3   881.3   413.8  888.79   451.5  912.85   460.9  915.04
#Mann= 3 , 0 , 0
       0      .1       0     228    .045       0     248      .1       0
Bank Sta=228,248
XS Rating Curve= 0 ,0
Exp/Cntr=0.3,0.1

Type RM Length L Ch R = 1 ,1279.1  ,250.4,245.2,240
XS GIS Cut Line= 4
     1723721.337      242033.341     1723797.191      242111.604
     1723956.125       242256.09     1724083.754      242313.884
#Sta/Elev= 30
     9.9  916.95    29.7  902.42    39.6  894.06    49.5  884.42    69.4   869.9
    79.3  865.17    89.2  862.05    99.1   854.3     148  820.73   157.8   812.5
   167.6  807.51   177.3  805.37   216.4  801.09   245.4  797.31   255.4  796.61
   265.4  797.14     275  798.61   294.5  802.79     314  808.03   333.8  815.18
   353.8  824.43   363.8  830.47   373.8  837.51   393.8   846.9   403.8  851.99
   413.9  857.77   433.9  870.57   443.9  877.52   453.9   887.3   463.9  898.02
#Mann= 3 , 0 , 0
       0      .1       0   245.4    .045       0   265.4      .1       0
Bank Sta=245.4,265.4
XS Rating Curve= 0 ,0
Exp/Cntr=0.3,0.1

Type RM Length L Ch R = 1 ,1033.9  ,243.1,240.7,238.2
XS GIS Cut Line= 4
     1723448.018      242350.005      1723659.93      242342.781
     1723814.048      242433.084     1723977.798       242520.98
#Sta/Elev= 30
    10.1  906.26    20.2  899.92    30.3  890.94    40.4  883.51    70.7  868.29
    90.9  857.34   111.1  837.36   121.2  830.76   131.3  825.04   141.4  820.38
   161.6  811.88   181.7  803.79   191.8  801.25   251.7  796.08   291.3  791.13
   301.3  790.58   311.3  791.02     341  794.69     351  797.88   370.8  809.95
   390.7  824.45   439.6  856.33   449.3  867.82   459.1  876.63   478.7  892.88
   498.3  910.01     508  917.64   537.4   938.1   547.2   945.7   576.5  962.59
#Mann= 3 , 0 , 0
       0      .1       0   291.3    .045       0   311.3     .08       0
Bank Sta=291.3,311.3
XS Rating Curve= 0 ,0
Exp/Cntr=0.3,0.1

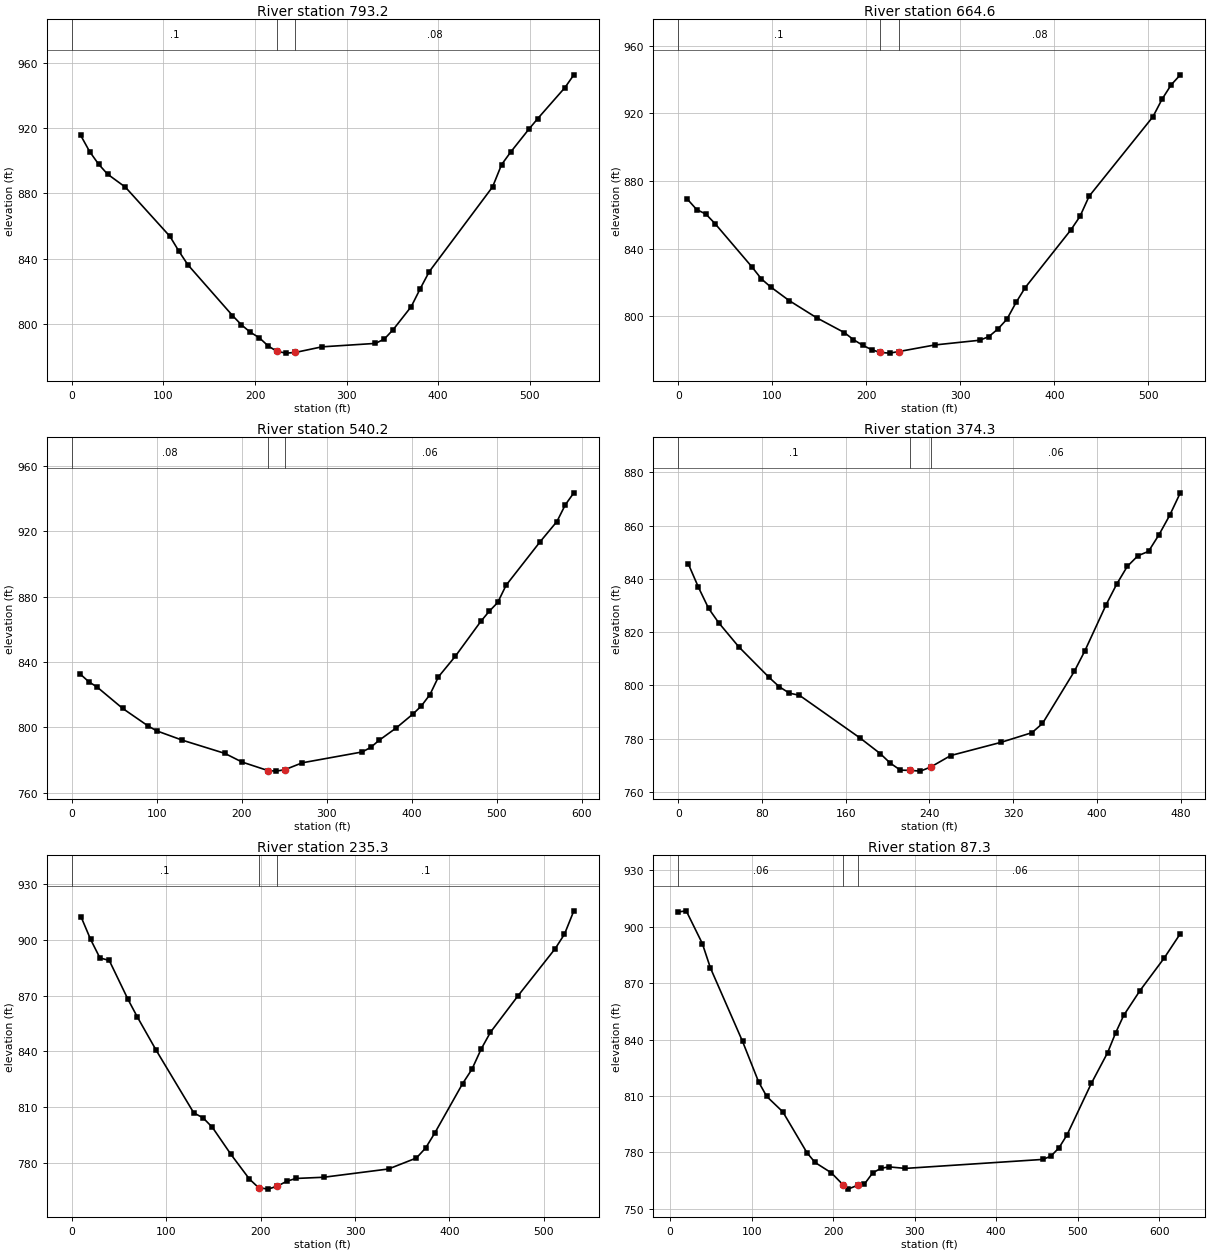
Type RM Length L Ch R = 1 ,793.2   ,129.8,128.6,127.5
XS GIS Cut Line= 4
     1723392.632      242448.737     1723535.914      242549.877
     1723702.072      242631.752     1723881.475      242685.934
#Sta/Elev= 30
     9.7  915.56    19.5   905.6    29.2  897.96      39  891.84    58.5  883.87
   107.2  853.76   116.9  844.76   126.7  836.45   175.4  805.44   185.1  799.81
   194.9  795.21   204.6  791.91   214.4  786.83   223.9  783.56   233.9  782.47
   243.9  782.87   272.9   786.3   331.4  788.41   341.1  791.04   350.9   796.9
   370.5  810.87   380.3   821.8   390.2  832.28   459.3  884.03   469.1  897.61
     479  905.26   498.7  919.14   508.6  925.77   538.2  944.64     548  952.49
#Mann= 3 , 0 , 0
       0      .1       0   223.9    .045       0   243.9     .08       0
Bank Sta=223.9,243.9
XS Rating Curve= 0 ,0
Exp/Cntr=0.3,0.1

Type RM Length L Ch R = 1 ,664.6   ,123.9,124.4,124.9
XS GIS Cut Line= 4
     1723351.695      242563.121     1723491.364      242671.485
     1723651.502      242736.504     1723832.109      242773.829
#Sta/Elev= 30
     9.8  869.16    19.6  863.08    29.5  860.35    39.3  854.64    78.6  828.97
    88.4  822.04    98.2   817.3   117.9  809.21   147.3  798.97   176.8  790.19
   186.4  786.03     196   782.8   205.6  780.12   214.8  778.47   224.8  778.07
   234.8  779.02   272.8   782.9   320.8  785.71   330.4  787.87     340  792.35
   349.6  798.17   359.3  808.06     369  816.86   417.6  851.03   427.3  859.03
     437  870.96   504.9  918.04   514.6  928.43   524.3  936.92     534  942.84
#Mann= 3 , 0 , 0
       0      .1       0   214.8    .045       0   234.8     .08       0
Bank Sta=214.8,234.8
XS Rating Curve= 0 ,0
Exp/Cntr=0.3,0.1

Type RM Length L Ch R = 1 ,540.2   ,144.8,166,187.1
XS GIS Cut Line= 4
     1723287.881      242667.873     1723410.693      242770.217
     1723568.423      242838.848      1723823.68      242795.502
#Sta/Elev= 30
      10   832.6      20  827.94      30  824.58    59.9  811.58    89.9   800.8
    99.9  797.85   129.9  792.16   180.1  784.04   200.3  778.75   230.8  773.52
   240.8  773.17   250.8  774.06   271.2  778.27   341.8  784.92   351.8  787.71
   361.8  792.12   381.7  799.59   401.6   808.2   411.5  813.19   421.5  820.08
   431.5  830.95   451.4  843.57   481.3  864.87   491.2  871.07   501.2  876.47
   511.1  887.05     551   913.6   570.9  926.07   580.8  936.35   590.8  943.64
#Mann= 3 , 0 , 0
       0     .08       0   230.8    .045       0   250.8     .06       0
Bank Sta=230.8,250.8
XS Rating Curve= 0 ,0
Exp/Cntr=0.3,0.1

Type RM Length L Ch R = 1 ,374.3   ,137.5,139,140.4
XS GIS Cut Line= 4
      1723269.82      242677.506     1723322.798      242832.827
     1723374.572      242988.149     1723425.142      243131.431
#Sta/Elev= 30
     9.7  845.55    19.3  836.83      29  828.92    38.6  823.55    57.9  814.46
    86.9  802.97    96.5  799.52   106.2  797.09   115.8   796.3   173.7  780.28
     193  774.42   202.6  770.84   212.3   768.2   221.5  768.11   231.5  767.83
   241.5  769.42   260.4  773.68   308.6  778.65     338  782.26   348.1  785.71
   378.5  805.26   388.6  812.98   408.9  830.29     419     838   429.1  844.65
   439.3  848.67   449.4   850.3   459.5   856.6   469.6   863.8   479.8  872.28
#Mann= 3 , 0 , 0
       0      .1       0   221.5    .045       0   241.5     .06       0
Bank Sta=221.5,241.5
XS Rating Curve= 0 ,0
Exp/Cntr=0.3,0.1

Type RM Length L Ch R = 1 ,235.3   ,136.6,148,159.5
XS GIS Cut Line= 4
     1723165.068      242737.708     1723193.965      242873.765
     1723255.371      243101.329     1723391.428      243179.592
#Sta/Elev= 30
     9.9  912.38    19.9  900.35    29.8  890.34    39.7  888.98    59.6  867.97
    69.5  858.49    89.4  840.62   129.2  806.92   139.1   804.2   148.9  799.14
   168.6  784.55   188.2  771.25   197.8  766.68   207.8  765.85   217.8  767.45
   227.5  770.05   237.3  771.59   266.8  772.24   335.5   776.7     365   782.6
   374.8  787.99   384.6  796.14     414  822.68   423.8  830.33   433.7  841.34
   443.5  850.33   472.9   870.1   512.1  895.36   521.9  903.15   531.8  915.69
#Mann= 3 , 0 , 0
       0      .1       0   197.8    .045       0   217.8      .1       0
Bank Sta=197.8,217.8
XS Rating Curve= 0 ,0
Exp/Cntr=0.3,0.1

Type RM Length L Ch R = 1 ,87.3    ,87.2,87.3,87.3
XS GIS Cut Line= 4
     1723154.767      242748.544       1723075.3      242907.478
     1723059.647      242986.945     1723373.903      243177.184
#Sta/Elev= 30
     9.9  907.89    19.7  908.51    39.5  891.09    49.4  878.12    88.8   839.1
   108.6  817.47   118.5   809.8   138.2  801.64   167.8  779.93   177.7  774.72
   197.9  769.15  212.59  762.62   218.2  760.52  231.05  762.75   238.4  763.23
   248.6  769.18   258.7   771.6   268.6  772.35   288.5  771.54   457.3  776.32
   467.2  778.04   477.1  782.47     487  789.36   516.8  816.74   536.7  833.01
   546.6  843.57   556.5   852.9   576.4  866.01   606.2  883.39     626  896.36
#Mann= 3 , 0 , 0
     9.9     .06       0  212.59    .045       0  231.05     .06       0
Bank Sta=212.59,231.05
XS Rating Curve= 0 ,0
Exp/Cntr=0.3,0.1

Chan Stop Cuts=-1
Use User Specified Reach Order=0